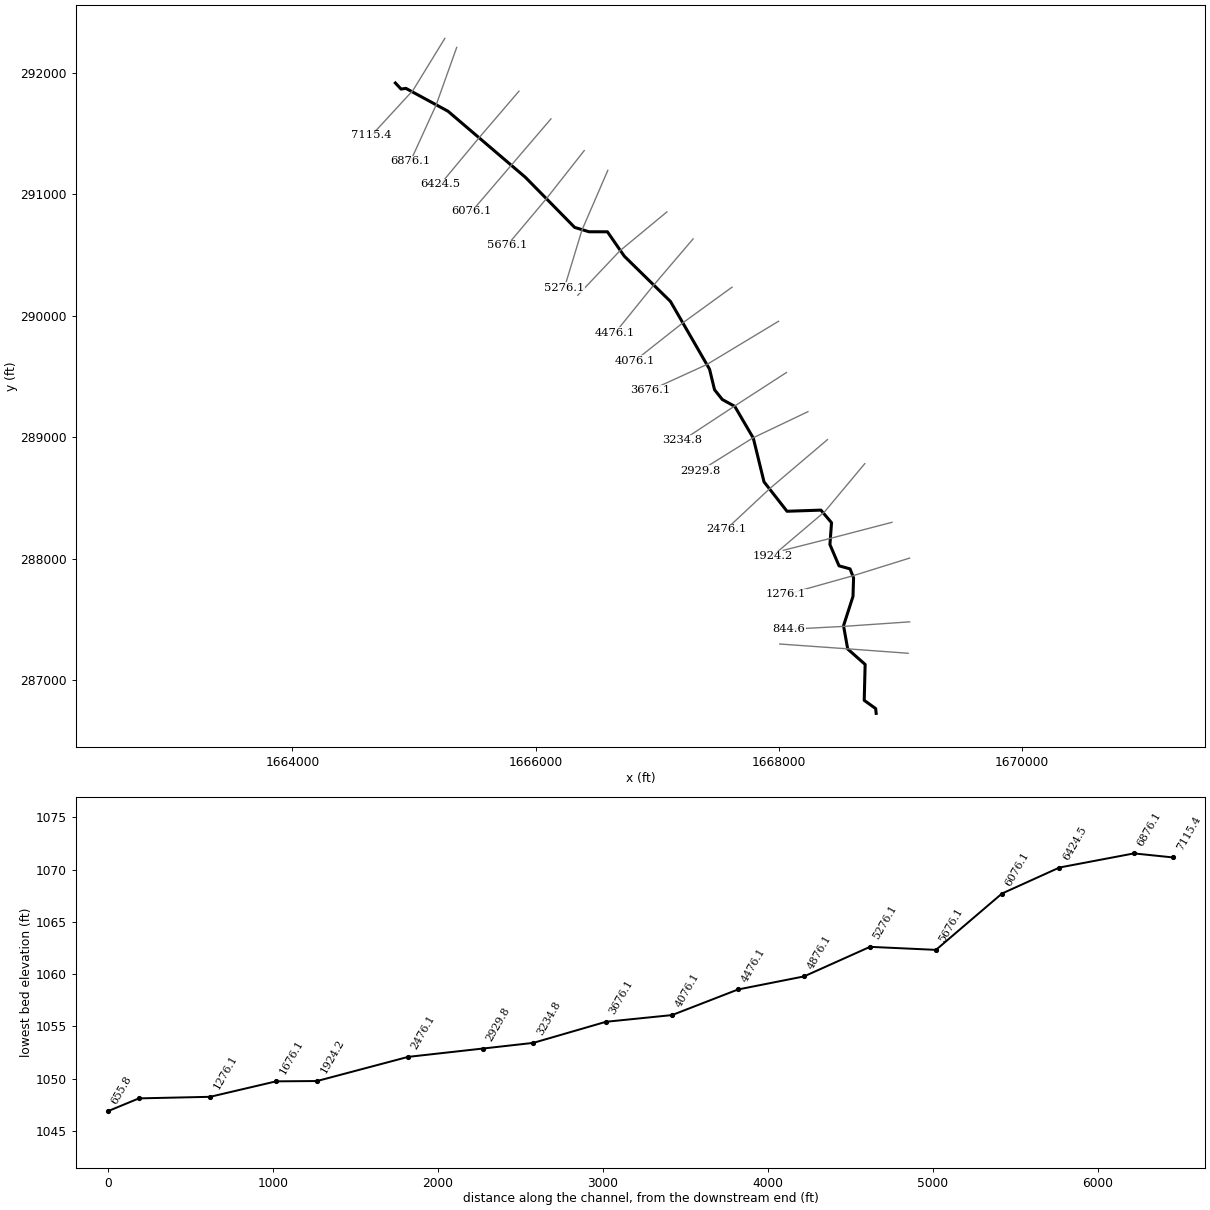
--- JacobsRn.prj (project) ---

Proj Title=JacobsRn
Current Plan=p01
Default Exp/Contr=0,0
English Units
Geom File=g01
Flow File=f01
Plan File=p01
BEGIN DESCRIPTION:
END DESCRIPTION:
DSS Export Rating Curves= 0
DSS Export Rating Curve Sorted= 0
DSS Export Volume Flow Curves= 0
DXF OffsetX= 0
DXF OffsetY= 0
DXF ScaleX= 0
DXF ScaleY= 0

--- JacobsRn.p01 (plan) ---

Plan Title=Floodplain
Program Version=4.00
Geom File=g01
Flow File=f01
K Sum by GR=0
Std Step Tol=0.01
Critical Tol=0.01
Num of Std Step Trials=20
Max Error Tol=0.3
Flow Tol Ratio=0.001
Split Flow NTrial=30
Split Flow Tol=0.02
Split Flow Ratio=0.02
Log Output Level=0
Friction Slope Method=1
Unsteady Friction Slope Method=2
Unsteady Bridges Friction Slope Method=1
Global Log Level=0
CheckData=False
Run HTab=0
Run UNet=0
Run PostProcess=0
UNET Theta=0
UNET Theta Warmup=0
UNET ZTol=0
UNET ZSATol=0
UNET MxIter=0
UNET MaxInSteps=0
UNET DtIC=0
UNET DtMin=0
UNET MaxCRTS=0
UNET WFStab=0
UNET SFStab=0
UNET WFX=0
UNET SFX=0
UNET DSS MLevel=0
UNET DZMax Abort=0
UNET Convert EG Bridges=0
UNET Use Existing IB Tables=0
UNET Froude Limit=0
UNET Froude Power=0
Write IC File=0
Echo Input=False
Echo Output=False
Write Detailed=0

--- JacobsRn.f01 (steady flow) ---

Flow Title=NFF Regression Equation
Program Version=4.00
Number of Profiles=1
Profile Names=P100yr
River Rch & RM=JacobsRn,Main      ,7115.4
622.9331
River Rch & RM=JacobsRn,Main      ,6876.1
874.2293
River Rch & RM=JacobsRn,Main      ,6076.1
896.6119
River Rch & RM=JacobsRn,Main      ,4476.1
989.5184
Boundary for River Rch & Prof#=JacobsRn,Main      ,1
Up Type=0
Dn Type=3
Dn Slope=0.002762

--- JacobsRn.g01 (geometry) ---

Geom Title=USGS 3m DEM
Program Version=4.00

River Reach=JacobsRn        ,Main
Reach XY= 30
     1664846.474      291918.589     1664893.131      291868.564
     1664933.049      291874.268      1665279.08       291686.09
     1665915.674       291141.51     1666320.546      290728.863
      1666438.74      290692.834     1666590.113      290692.574
     1666729.047      290491.434     1667108.515      290118.702
     1667429.925       289560.39      1667470.88      289391.131
     1667534.898      289310.525     1667637.284      289254.274
     1667789.692      288992.742      1667877.82      288632.194
     1668066.778      288389.843     1668345.676      288399.172
     1668433.027      288295.493     1668419.807      288115.607
     1668494.457      287940.388     1668585.176      287914.989
     1668614.205      287840.855     1668609.542      287688.708
      1668531.78      287446.613     1668565.997      287254.805
     1668709.333      287127.798     1668701.816      286831.789
     1668795.908       286764.14     1668800.053      286724.483

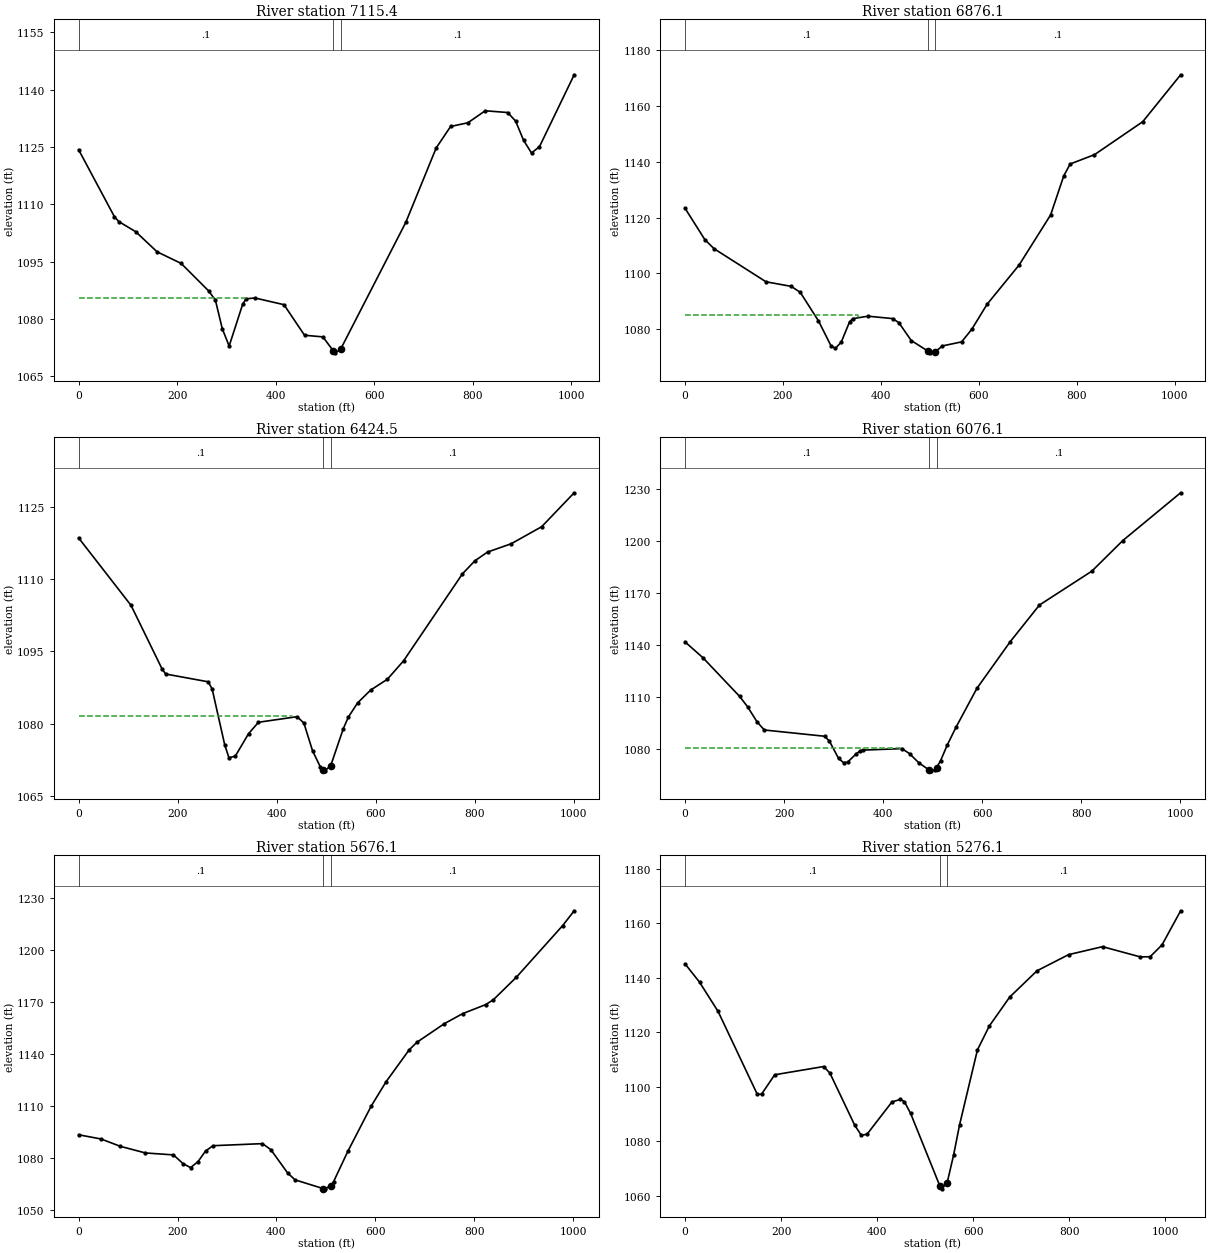
Type RM Length L Ch R = 1 ,7115.4  ,230.644,239.332,246.112
XS GIS Cut Line= 3
     1665253.281      292286.579     1664991.264      291857.921
     1664650.588      291487.321
#Sta/Elev= 30
       0 1124.26    72.7 1106.73    81.4 1105.49   115.9 1102.82   159.1 1097.58
   208.1 1094.53   263.7 1087.37   277.6 1084.94   291.5 1077.48   305.5 1072.93
   333.3 1083.99   340.4 1085.28   357.7  1085.5   416.8 1083.74   458.5 1075.75
   495.9 1075.32   516.6 1071.71   521.3 1071.15   531.6 1072.06   664.1 1105.28
   725.7 1124.72     755 1130.34   790.1 1131.31   825.2 1134.45   870.8 1133.99
     887 1131.75   903.1 1126.72   919.2 1123.41   935.4 1125.06  1005.8 1143.86
#Mann= 3 , 0 , 0
       0      .1       0   516.6    .045       0   531.6      .1       0
#XS Ineff= 2 , 0
          343.31 1085.53
Permanent Ineff=
       F       F
Bank Sta=516.6,531.6
XS Rating Curve= 0 ,0
Exp/Cntr=0.3,0.1

Type RM Length L Ch R = 1 ,6876.1  ,459.862,451.555,445.626
XS GIS Cut Line= 3
     1665350.654      292211.811     1665181.701      291737.508
     1664970.572       291274.43
#Sta/Elev= 30
       0 1123.34    40.2 1112.16    59.1 1108.88   165.3 1097.01   216.8 1095.37
   235.3 1093.22   272.5 1082.99   298.1 1074.06   306.8  1073.1     319 1075.38
   335.9 1082.59   342.2 1083.78   373.7 1084.68   424.2 1083.81   436.8 1082.33
     462 1075.95     496 1072.18   499.8 1071.54     511 1071.93   525.7 1074.02
   564.9 1075.47   585.5 1079.93   617.1 1088.99   682.3    1103   746.8 1120.99
   773.7 1135.02   786.7 1139.24   836.4 1142.58     935  1154.4  1012.4 1171.22
#Mann= 3 , 0 , 0
       0      .1       0     496    .045       0     511      .1       0
#XS Ineff= 2 , 0
          352.88 1084.97
Permanent Ineff=
       F       F
Bank Sta=496,511
XS Rating Curve= 0 ,0
Exp/Cntr=0.3,0.1

Type RM Length L Ch R = 1 ,6424.5  ,348.449,348.445,348.121
XS GIS Cut Line= 3
     1665862.657      291851.009     1665537.057      291470.154
     1665217.605      291085.208
#Sta/Elev= 30
       0 1118.57   105.9 1104.56   168.9 1091.29     176  1090.3   261.6 1088.69
   269.7 1087.23   295.2 1075.59   303.7 1072.92   316.5 1073.23   343.4 1077.92
   363.4 1080.28   441.5 1081.44   455.2 1080.11   472.7 1074.34   488.4 1071.01
   494.3 1070.45   497.3 1070.19   509.3 1071.25   534.8 1078.95   545.1 1081.37
   563.7  1084.3   590.1 1086.97   623.8 1089.21   656.7 1093.06   775.6 1111.12
   800.9 1113.84   826.2 1115.63   874.2 1117.37   935.6  1120.9  1001.3 1127.95
#Mann= 3 , 0 , 0
       0      .1       0   494.3    .045       0   509.3      .1       0
#XS Ineff= 2 , 0
          431.53 1081.57
Permanent Ineff=
       F       F
Bank Sta=494.3,509.3
XS Rating Curve= 0 ,0
Exp/Cntr=0.3,0.1

Type RM Length L Ch R = 1 ,6076.1  ,399.074,400,400.197
XS GIS Cut Line= 3
     1666125.779       291622.86     1665800.651      291242.344
     1665475.523      290861.829
#Sta/Elev= 30
       0  1141.9    35.8  1132.9   110.1 1110.58   126.4 1104.52   145.4 1095.89
     160 1091.22   281.8 1087.62   291.6 1084.79   309.9 1074.89     320 1072.42
   328.2 1072.68   345.3 1077.42   353.7  1079.2   359.9 1079.64   437.9  1080.5
   453.6 1077.56   471.6 1072.44     493 1068.17   496.9  1067.7   505.3  1068.4
     508 1069.58   516.1 1073.54   529.2 1082.34   547.3 1092.84   589.5 1115.22
   656.6 1142.01   715.8 1163.18   821.7 1182.69   884.3 1200.33    1001 1227.81
#Mann= 3 , 0 , 0
       0      .1       0     493    .045       0     508      .1       0
#XS Ineff= 2 , 0
          434.72 1080.79
Permanent Ineff=
       F       F
Bank Sta=493,508
XS Rating Curve= 0 ,0
Exp/Cntr=0.3,0.1

Type RM Length L Ch R = 1 ,5676.1  ,394.304,400,409.03
XS GIS Cut Line= 3
     1666399.081      291361.127     1666088.998      290966.241
     1665767.441      290582.988
#Sta/Elev= 30
       0 1093.46    45.3 1091.03    84.4 1086.79   135.1 1082.98   191.8 1081.86
   211.4 1076.79   226.5 1074.54   241.6 1078.03   256.7 1084.09   271.8 1087.16
   371.9 1088.35   388.8 1084.88   422.7 1071.49   437.8 1067.48   494.6 1062.46
   498.2 1062.31   509.6 1064.04   515.6 1066.38   544.6 1083.93   591.8 1109.97
   622.1 1124.08   668.6 1142.36   684.1 1146.71   739.6 1157.42   776.6 1163.21
   823.6 1168.46   839.1 1171.28   885.6 1184.26   979.1 1213.95  1002.4 1222.49
#Mann= 3 , 0 , 0
       0      .1       0   494.6    .045       0   509.6      .1       0
Bank Sta=494.6,509.6
XS Rating Curve= 0 ,0
Exp/Cntr=0.3,0.1

Type RM Length L Ch R = 1 ,5276.1  ,411.361,400,388.811
XS GIS Cut Line= 3
      1666593.27      291198.688     1666379.967      290704.298
     1666236.623      290231.757
#Sta/Elev= 30
       0  1145.1      30 1138.43    68.8 1127.65   150.4 1097.26   159.3 1097.33
   186.6 1104.44   288.6 1107.46   301.6 1105.06   353.3 1085.94   367.2  1082.2
   379.1 1082.66   430.9 1094.48   448.5  1095.4   456.7  1094.6   469.7 1090.28
   530.9 1063.55   534.3  1062.6   545.9 1064.85   559.3 1075.01   571.7 1086.06
   608.9 1113.55   633.7 1122.33   676.1 1132.93     733 1142.58   798.8  1148.5
   869.5 1151.43   948.2 1147.67   968.7 1147.74   993.5 1152.09  1032.2 1164.59
#Mann= 3 , 0 , 0
       0      .1       0   530.9    .045       0   545.9      .1       0
Bank Sta=530.9,545.9
XS Rating Curve= 0 ,0
Exp/Cntr=0.3,0.1

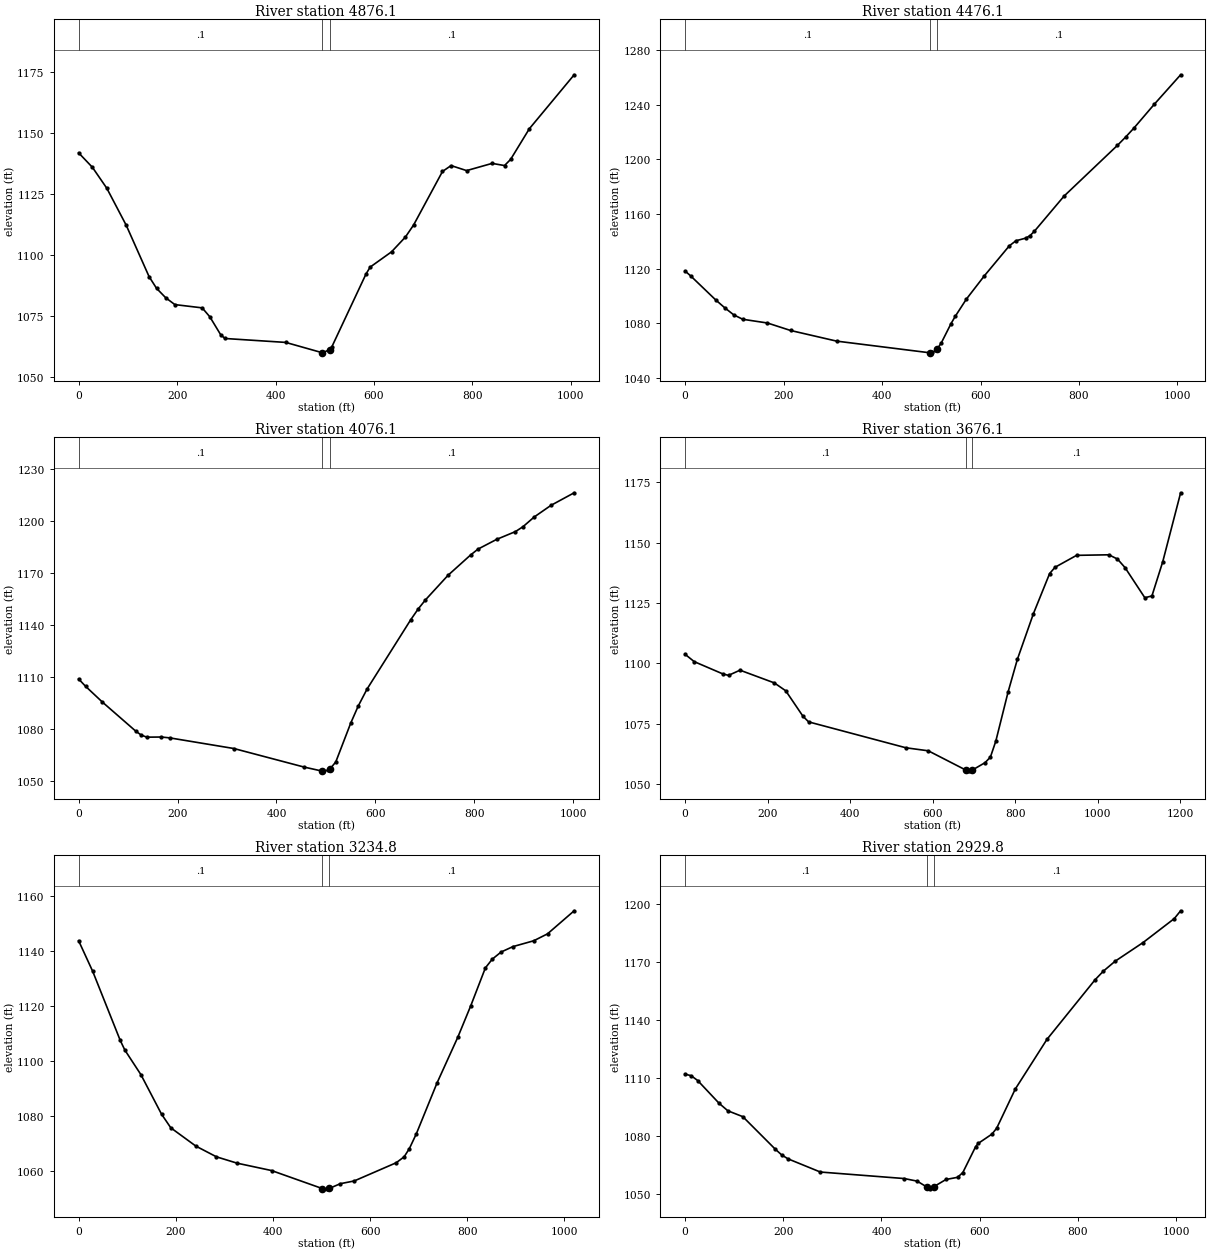
Type RM Length L Ch R = 1 ,4876.1  ,396.089,400,401.718
XS GIS Cut Line= 3
     1667079.362      290856.627     1666692.818       290536.05
     1666346.261      290169.363
#Sta/Elev= 30
       0 1141.86    28.1 1135.89    57.2 1127.34    96.8 1112.09   143.1 1091.06
   158.3 1086.25   176.9 1082.38   195.5 1079.57     251 1078.23   266.5 1074.57
   288.5 1067.23   297.3 1065.66   420.7 1064.05   494.7 1059.83   495.7 1059.77
   509.7 1061.08   514.6 1062.32   583.7 1092.08   592.2 1094.96   635.6 1101.22
   663.7 1107.26   680.5 1112.24   739.2 1134.22   756.6 1136.63   788.2 1134.57
     840 1137.53   865.2 1136.64   877.6 1139.17   915.6 1151.74  1006.7  1173.9
#Mann= 3 , 0 , 0
       0      .1       0   494.7    .045       0   509.7      .1       0
Bank Sta=494.7,509.7
XS Rating Curve= 0 ,0
Exp/Cntr=0.3,0.1

Type RM Length L Ch R = 1 ,4476.1  ,405.316,400,395.026
XS GIS Cut Line= 3
     1667294.473      290633.709     1666967.251       290249.14
     1666652.221       289859.03
#Sta/Elev= 30
       0 1118.36    11.5 1114.74    62.2 1097.21    80.5 1091.48    98.8  1086.3
   117.1 1083.07   167.3 1080.34   214.1 1074.89   307.6  1067.1   497.4 1058.54
     498 1058.52   501.9 1058.83   510.2 1060.31   512.4 1061.51   520.7 1066.06
   540.2 1079.97   548.6 1085.19   571.2 1097.79   607.7 1114.83   658.4 1136.78
   671.9 1140.51   692.2 1142.47   700.6 1144.27   709.6 1147.55   769.6 1173.16
   877.9 1210.25   894.8 1216.41   911.7 1223.01   952.7 1240.29  1006.4 1261.93
#Mann= 3 , 0 , 0
       0      .1       0   497.4    .045       0   512.4      .1       0
Bank Sta=497.4,512.4
XS Rating Curve= 0 ,0
Exp/Cntr=0.3,0.1

Type RM Length L Ch R = 1 ,4076.1  ,401.911,400,394.564
XS GIS Cut Line= 3
     1667614.987      290236.308     1667210.183      289942.285
     1666816.844      289631.113
#Sta/Elev= 30
       0 1108.95      14 1104.75      48 1095.67     116  1078.8   126.5 1076.68
   137.8 1075.46   167.1 1075.54     184 1075.06   313.9 1068.92     456 1058.23
     490 1056.07   492.8 1056.07   504.8  1056.3   507.8 1057.05   519.9 1061.18
   550.2  1083.6   565.3 1093.38   583.1 1103.14   671.3    1143   686.4 1149.23
   701.2 1154.49     747  1168.7   792.4 1180.33   807.5 1183.74   845.1 1189.33
   883.2 1193.83   898.4 1196.63   921.2 1202.25     955 1208.93  1001.9 1216.17
#Mann= 3 , 0 , 0
       0      .1       0   492.8    .045       0   507.8      .1       0
Bank Sta=492.8,507.8
XS Rating Curve= 0 ,0
Exp/Cntr=0.3,0.1

Type RM Length L Ch R = 1 ,3676.1  ,440.504,441.261,444.723
XS GIS Cut Line= 3
     1667997.309      289955.286     1667407.878      289599.049
     1666941.548      289385.946
#Sta/Elev= 30
       0 1103.71    22.1 1100.67    91.4 1095.59   105.3 1094.98   133.1 1097.13
   216.3 1091.86     244 1088.59   285.7 1078.06   299.5 1075.71   535.4 1064.98
   589.6 1063.73   681.2  1055.7     688 1055.43   696.2 1055.74   727.2 1058.81
   740.2 1061.12   753.3 1067.73   783.1 1088.12   805.5 1101.59   844.6  1120.6
   883.8 1137.17   896.9 1139.76   949.1  1144.7  1027.4 1144.93  1048.3 1143.16
  1066.6 1139.62  1114.6 1127.14  1131.8 1127.89  1157.9 1141.99  1201.4 1170.62
#Mann= 3 , 0 , 0
       0      .1       0   681.2    .045       0   696.2      .1       0
Bank Sta=681.2,696.2
XS Rating Curve= 0 ,0
Exp/Cntr=0.3,0.1

Type RM Length L Ch R = 1 ,3234.8  ,307.982,305.074,304.58
XS GIS Cut Line= 3
     1668062.235      289533.129     1667642.209      289260.768
     1667208.299      288975.048
#Sta/Elev= 30
       0 1143.72    29.1 1132.53    85.7 1107.42    95.2 1103.91   128.2 1094.98
   170.6 1080.61   189.7 1075.63   241.4 1068.96   283.8 1065.06   326.3 1062.75
   397.1 1060.07   501.3 1053.53   510.3 1053.41   516.3 1053.58   538.7 1055.28
   567.3 1056.28   653.8 1062.91   670.1 1065.07   680.9 1068.08   695.1 1073.41
   737.7 1091.92   780.4 1108.54   807.3 1120.09   837.3 1133.83   851.5 1137.02
   869.7 1139.62   894.1 1141.59   936.8 1143.71   965.2 1146.23  1020.1 1154.63
#Mann= 3 , 0 , 0
       0      .1       0   501.3    .045       0   516.3      .1       0
Bank Sta=501.3,516.3
XS Rating Curve= 0 ,0
Exp/Cntr=0.3,0.1

Type RM Length L Ch R = 1 ,2929.8  ,447.682,453.665,458.205
XS GIS Cut Line= 3
      1668238.94      289210.267     1667787.934      288995.057
     1667355.554      288725.004
#Sta/Elev= 30
       0 1112.18    12.4 1111.35    25.6 1108.88    69.3 1097.09    87.1 1093.22
   117.6 1090.18   183.4 1073.45   196.6 1070.44   209.7 1068.37   275.5 1061.56
   446.5 1058.19   472.8 1056.85   491.9  1053.9   499.1 1052.87   506.9 1054.01
   531.4  1057.7   555.1 1058.83   565.8  1061.3   591.7 1074.59   597.1 1076.35
   625.1 1081.17   634.8 1084.24   672.6 1104.45   737.1 1130.12   835.1 1160.93
   851.9 1165.38     876 1170.54     933 1180.21   996.6  1192.6  1009.5 1196.63
#Mann= 3 , 0 , 0
       0      .1       0   491.9    .045       0   506.9      .1       0
Bank Sta=491.9,506.9
XS Rating Curve= 0 ,0
Exp/Cntr=0.3,0.1

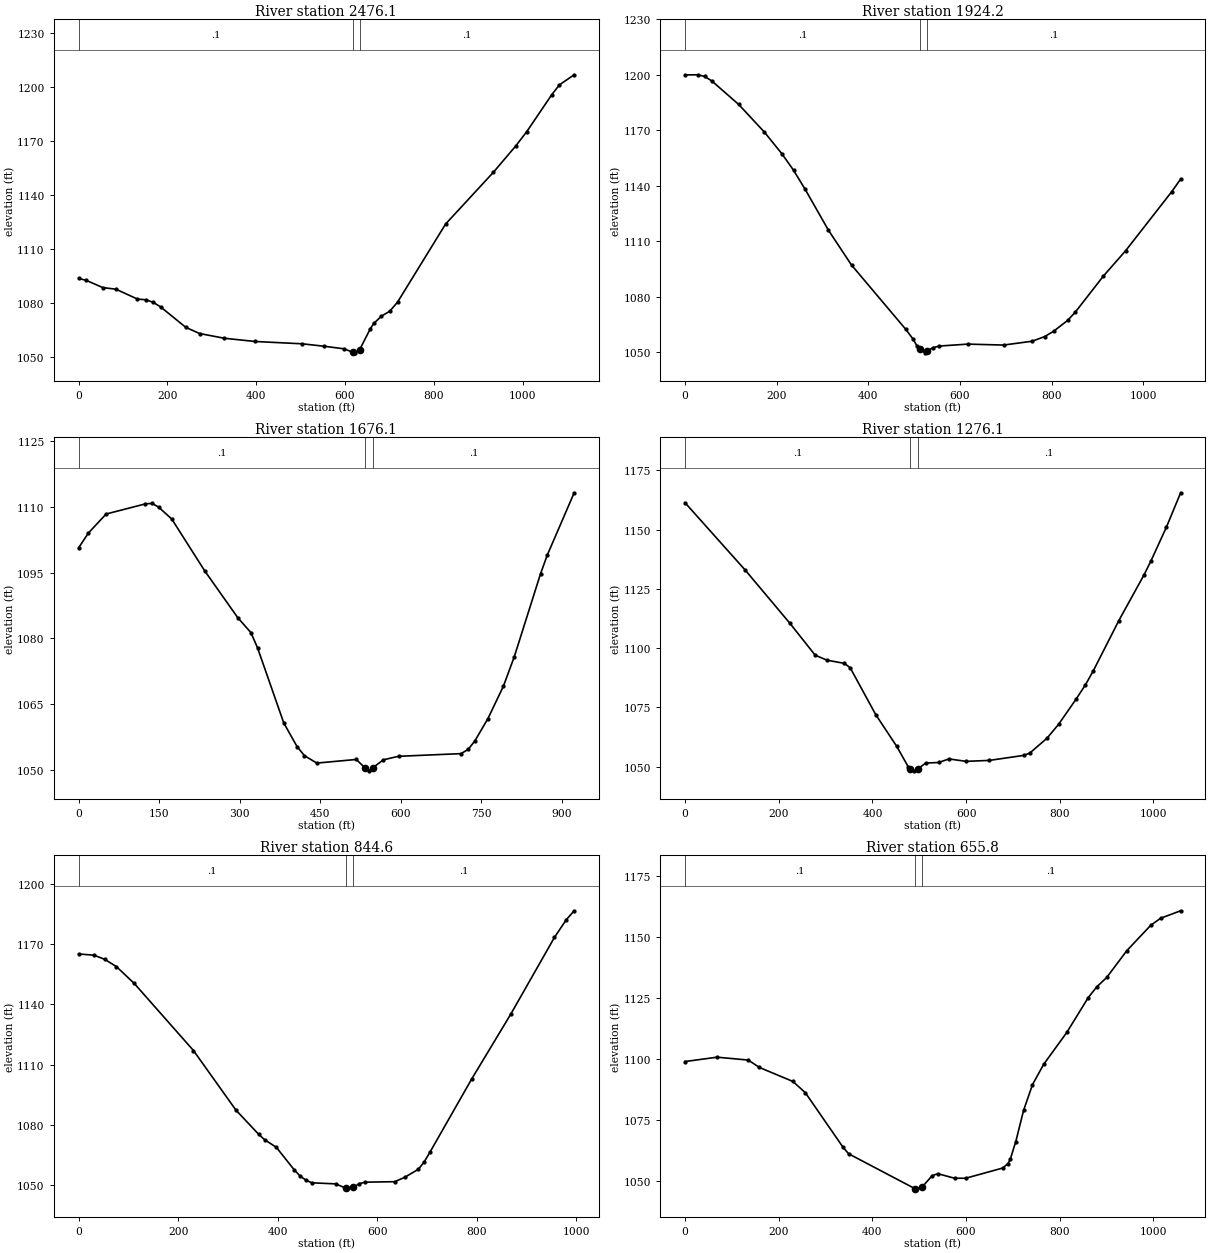
Type RM Length L Ch R = 1 ,2476.1  ,548.776,551.901,550.82
XS GIS Cut Line= 3
     1668399.781      288980.367     1667923.604      288575.291
     1667565.296      288239.699
#Sta/Elev= 30
       0 1093.47    16.6 1092.48    54.4 1088.39      84  1087.5   132.3 1082.02
   151.3 1081.61   168.2 1080.17     185 1077.57   241.5 1066.23   272.6 1062.81
   328.2 1060.19   397.3 1058.39   503.5  1057.1   553.2 1055.74   597.7 1054.31
   617.7 1052.39     623 1052.07   632.7  1053.7   656.6 1065.31     665 1068.51
   681.8 1072.46   700.9 1075.28   718.3 1080.31   826.6 1123.81   933.8 1152.49
   984.2 1167.15  1009.4 1175.24  1065.6 1195.78    1083 1201.28  1116.1 1206.87
#Mann= 3 , 0 , 0
       0      .1       0   617.7    .045       0   632.7      .1       0
Bank Sta=617.7,632.7
XS Rating Curve= 0 ,0
Exp/Cntr=0.3,0.1

Type RM Length L Ch R = 1 ,1924.2  ,261.29,248.099,237.889
XS GIS Cut Line= 3
     1668706.314      288782.077     1668376.434       288386.08
     1667945.025      288019.327
#Sta/Elev= 30
       0 1199.98    27.5 1200.07    42.8 1199.16    58.4 1196.71     117 1184.02
   172.7 1169.19   211.5  1157.3   236.8 1148.43   262.1 1138.14   312.6 1116.15
   363.2 1097.23   481.2  1062.6   498.1 1057.03   506.5 1053.26     513 1051.82
   523.2 1049.76     528 1050.51   540.2  1052.5   554.7 1053.43   617.1 1054.48
     695 1053.96   757.3 1056.03   784.5 1058.51   804.1 1061.39   834.8 1067.25
   851.9 1071.82   913.1  1091.3   961.4 1104.92  1062.4 1136.95  1081.6 1143.69
#Mann= 3 , 0 , 0
       0      .1       0     513    .045       0     528      .1       0
Bank Sta=513,528
XS Rating Curve= 0 ,0
Exp/Cntr=0.3,0.1

Type RM Length L Ch R = 1 ,1676.1  ,398.998,400,400.486
XS GIS Cut Line= 3
     1668929.921      288298.664     1668406.786      288162.092
     1668036.384      288067.967
#Sta/Elev= 30
       0 1100.66      18 1104.01    51.2 1108.38   124.5  1110.7   136.7 1110.81
     149 1109.95   173.5 1107.22   234.9 1095.38   296.2 1084.73   320.8  1081.3
   333.1 1077.84   382.1 1060.64   406.7 1055.28   420.4 1053.21   443.5  1051.5
   517.1 1052.33   533.2  1050.4   540.7 1049.73   548.2 1050.46   567.5 1052.25
   595.7 1053.05   712.2 1053.66   725.4 1054.63   737.7 1056.53   762.2 1061.66
   791.1 1069.09   811.2 1075.75   860.1 1094.71   872.4 1098.91   922.8 1113.23
#Mann= 3 , 0 , 0
       0      .1       0   533.2    .045       0   548.2      .1       0
Bank Sta=533.2,548.2
XS Rating Curve= 0 ,0
Exp/Cntr=0.3,0.1

Type RM Length L Ch R = 1 ,1276.1  ,436.751,431.45,426.509
XS GIS Cut Line= 3
     1669074.586       288003.85     1668608.144       287858.09
     1668059.966      287704.224
#Sta/Elev= 30
       0 1161.34   128.4 1132.93   223.3 1110.61   277.7 1097.05   302.6 1094.95
   339.9  1093.6   352.4 1091.76   407.2 1071.91   451.9 1058.56   476.7 1049.84
   481.2  1049.1   488.7 1048.25   496.2 1048.97   513.8 1051.54   541.6 1051.77
   563.2 1053.27   600.2 1052.25   649.5 1052.65   723.5 1054.78   735.8 1055.73
   772.8 1062.04   797.5 1067.89   834.5 1078.42   854.5 1084.45   871.5 1090.45
   925.9 1111.59   979.7 1130.88   994.8 1136.88  1027.8 1151.15    1058 1165.56
#Mann= 3 , 0 , 0
       0      .1       0   481.2    .045       0   496.2      .1       0
Bank Sta=481.2,496.2
XS Rating Curve= 0 ,0
Exp/Cntr=0.3,0.1

Type RM Length L Ch R = 1 ,844.6   ,200.53,188.882,185.995
XS GIS Cut Line= 3
     1669075.365      287478.642     1668528.379      287440.964
      1668081.32       287417.37
#Sta/Elev= 30
       0 1165.04    30.7 1164.44    52.3 1162.39    76.1 1158.73   111.8 1150.36
   230.8 1116.97     316 1087.35   361.7 1075.29   373.6  1072.6   397.4 1068.77
   433.1 1057.63     445 1054.52   456.9 1052.41   468.8  1051.1   516.4 1050.57
   537.2 1048.45   540.2  1048.1   552.2 1048.78     564 1050.68   575.9 1051.43
   635.3 1051.66     655 1053.79   682.9 1057.84   694.8  1061.6   706.7  1066.6
   789.9 1102.74   868.4 1135.01   956.3 1173.27   980.1 1182.08     996 1186.55
#Mann= 3 , 0 , 0
       0      .1       0   537.2    .045       0   552.2      .1       0
Bank Sta=537.2,552.2
XS Rating Curve= 0 ,0
Exp/Cntr=0.3,0.1

Type RM Length L Ch R = 1 ,655.8   ,638.772,655.764,662.554
XS GIS Cut Line= 3
      1669062.98      287219.736     1668563.236      287256.399
     1668006.981      287295.993
#Sta/Elev= 30
       0 1098.95    68.4 1100.73   135.1 1099.54   158.9 1096.51   230.3  1090.8
   256.9  1086.2   337.5 1063.86   349.4 1061.21     491 1046.95   492.2 1046.87
     506 1047.54     528 1052.27   539.9 1053.06   575.6 1051.22   599.4  1051.2
   678.7 1055.39   689.8 1057.21   694.6 1058.88   706.5 1066.22   723.1 1078.93
   742.2 1089.51     766 1097.78   815.5 1110.86   861.2 1125.07   879.5 1129.49
   900.9 1133.37   943.6 1144.28   994.9  1154.7    1016 1157.57  1058.7 1160.62
#Mann= 3 , 0 , 0
       0      .1       0     491    .045       0     506      .1       0
Bank Sta=491,506
XS Rating Curve= 0 ,0
Exp/Cntr=0.3,0.1

Chan Stop Cuts=-1
Use User Specified Reach Order=0